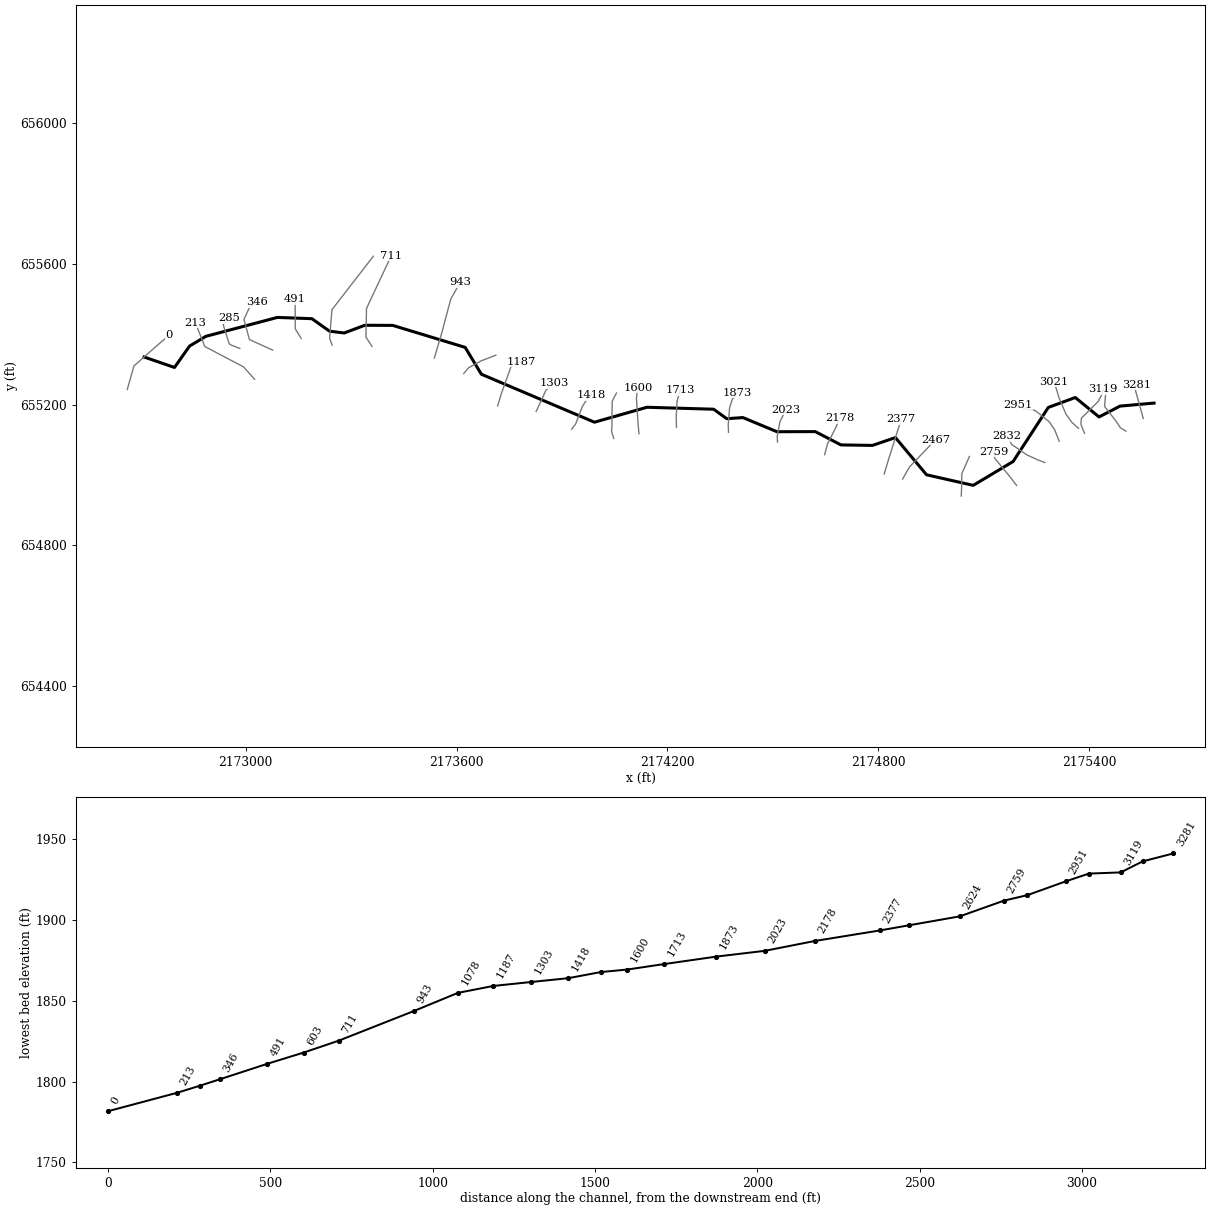
--- LIKANARV2A.prj (project) ---

Proj Title=LIKANARV2A
Current Plan=p01
Default Exp/Contr=0,0
English Units
Geom File=g01
Flow File=f01
Plan File=p01
BEGIN DESCRIPTION:
---------- MODELED AS PART OF WVEMD CTP PROGRAM, 2023----------
Stream Name: Little Kanawha River Tributary 2a
Flood Zone:  AFH
Upshur County, WV
HEC-RAS Version: RAS 6.3
Vertical Datum: NAVD88
Projection: NAD 1983 StatePlane West Virginia S FIPS 4702 (US Feet)
Terrain: 1-meter LIDAR (FEMA Region III 3DEP collected 2016-2018)
Land Use: 2019 NLCD
Hydrologic Method:
WV SIR2010-5033 regression equations
Additional Model Notes:
Coincident Peak with LIKANARVT2
END DESCRIPTION:
DSS File=dss
DSS Export Rating Curves= 0
DSS Export Rating Curve Sorted= 0
DSS Export Volume Flow Curves= 0
DXF OffsetX= 0
DXF OffsetY= 0
DXF ScaleX= 0
DXF ScaleY= 0

--- LIKANARV2A.p01 (plan) ---

Plan Title=Floodplain
Program Version=6.30
Short Identifier=Floodplain
Geom File=g01
Flow File=f01
Subcritical Flow
K Sum by GR= 0
Std Step Tol= 0.01
Critical Tol= 0.01
Num of Std Step Trials= 20
Max Error Tol= 0.3
Flow Tol Ratio= 0.001
Split Flow NTrial= 30
Split Flow Tol= 0.02
Split Flow Ratio= 0.02
Log Output Level= 0
Friction Slope Method= 1
Unsteady Friction Slope Method= 2
Unsteady Bridges Friction Slope Method= 1
Parabolic Critical Depth
Global Vel Dist= 0 , 0 , 0
Global Log Level= 0
CheckData=True
Encroach Param=-1 ,0,0, 0
Computation Interval=0.1SEC
Output Interval=1SEC
Instantaneous Interval=Max Profile
Mapping Interval=1HOUR
Computation Time Step Use Courant=        0
Computation Time Step Use Time Series=    0
Computation Time Step Count To Double=0
Computation Time Step Max Doubling=0
Computation Time Step Max Halving=0
Computation Time Step Residence Courant=0
Run HTab= 0
Run UNet= 0
Run Sediment= 0
Run PostProcess= 0
Run WQNet= 0
Run RASMapper=-1
UNET Theta= 0
UNET Theta Warmup= 0
UNET ZTol= 0
UNET ZSATol= 0
UNET MxIter= 0
UNET Max Iter WO Improvement= 0
UNET MaxInSteps= 0
UNET DtIC= 0
UNET DtMin= 0
UNET MaxCRTS= 0
UNET WFStab= 0
UNET SFStab= 0
UNET WFX= 1
UNET SFX= 1
UNET Gravity=32.17405
UNET 1D Methodology=Finite Difference
UNET DSS MLevel= 1
UNET Pardiso=0
UNET DZMax Abort= 0
UNET Use Existing IB Tables= 0
UNET Froude Reduction=False
UNET Froude Limit= 0
UNET Froude Power= 0
UNET D1 Cores= 0
UNET WindReference=Eulerian
UNET WindDragFormulation=Hsu (1988)
UNET D2 Coriolis=0
UNET D2 Cores= 0
UNET D2 Theta= 1
UNET D2 Theta Warmup= 1
UNET D2 Z Tol= 0.01
UNET D2 Volume Tol= 0.01
UNET D2 Max Iterations= 20
UNET D2 Equation= 0
UNET D2 RampUpFraction=0.1
UNET D2 TimeSlices= 1
UNET D2 Turbulence Formulation=Non-Conservative (original)
UNET D2 Eddy Viscosity=0.3
UNET D2 Transverse Eddy Viscosity=0.1
UNET D2 Smagorinsky Mixing=0
UNET D2 BCVolumeCheck=0
UNET D2 Cores=0
UNET D2 SolverType=PARDISO (Direct)
UNET D2 Minimum Iterations= 3
UNET D2 Maximum Iterations= 30
UNET D2 Restart Number= 10
UNET D2 Relaxation Coeff=1.3
UNET D2 SOR Precondition Iterations= 10
UNET D2 ILUT Maximum Fill= 8
UNET D2 ILUT Tolerance=1E-08
UNET D2 Convergence Tolerance=0.00001
UNET D1D2 MaxIter= 0
UNET D1D2 ZTol=0.01
UNET D1D2 QTol=0.1
UNET D1D2 MinQTol=1
DSS File=dss
Write IC File= 0
Write IC File at Fixed DateTime=0
Write IC File at Sim End=0
Echo Input=False
Echo Parameters=False
Echo Output=False
Write Detailed= 0
HDF Write Warmup=0
HDF Write Time Slices=0
HDF Flush=0
HDF Compression= 1
HDF Chunk Size= 1
HDF Spatial Parts= 1
HDF Use Max Rows=0
HDF Fixed Rows= 1
Calibration Method= 0
Calibration Iterations= 20
Calibration Max Change=0.05
Calibration Tolerance=0.2
Calibration Maximum=1.5
Calibration Minimum=0.5
Calibration Optimization Method= 1
WQ AD Non Conservative
WQ ULTIMATE=-1
WQ Max Comp Step=1HOUR
WQ Output Interval=15MIN
WQ Output Selected Increments= 0
WQ Output face flow=0
WQ Output face velocity=0
WQ Output face area=0
WQ Output face dispersion=0
WQ Output cell volume=0
WQ Output cell surface area=0
WQ Output cell continuity=0
WQ Output cumulative cell continuity=0
WQ Output face conc=0
WQ Output face dconc_dx=0
WQ Output face courant=0
WQ Output face peclet=0
WQ Output face adv mass=0
WQ Output face disp mass=0
WQ Output cell mass=0
WQ Output cell source sink temp=0
WQ Output nsm pathways=0
WQ Output nsm derived pathways=0
WQ Create Restart=0
WQ Fixed Restart=0
WQ System Summary=0
WQ Write To DSS=0
Sorting and Armoring Iterations= 10
XS Update Threshold= 0.02
Bed Roughness Predictor= 0
Hydraulics Update Threshold= 0.02
Energy Slope Method= 1
Volume Change Method= 1
Sediment Retention Method= 0
Sediment TS Multiplier= 1
Warm Up Method= 0
XS Weighting Method= 0
Number of US Weighted Cross Sections= 1
Number of DS Weighted Cross Sections= 1
Upstream XS Weight=0
Main XS Weight=1
Downstream XS Weight=0
Number of DS XS's Weighted with US Boundary= 1
Upstream Boundary Weight= 1
Weight of XSs Associated with US Boundary= 0
Number of US XS's Weighted with DS Boundary= 1
Downstream Boundary Weight= 0.5
Weight of XSs Associated with DS Boundary= 0.5
Percentile Method= 0
Sediment Output Level= 3
Mass or Volume Output= 0
Output Increment Type= 1
Profile and TS Output Increment= 1
Transport Output Increment 1
XS Output Flag= 0
XS Output Increment= 10
Read HDF5 Sediment Hotstart= 0
Sediment Hotstart Type= 0
Write Gradation File= 0
Read Gradation Hotstart= 0
Write HDF5 File= 1
Write Binary Output= 1
Write DSS Sediment File= 0
DSS Sediment Output Type= 1
SV Curve= 0
Specific Gage Flag= 0
Subcell Erosion Methods= 0
Subcell Deposition Methods= 0
Advection Scheme= 1
Matrix Solver= 0
Implicit Weighting Factor= 1
Maximum Outer Loop Convergence Iterations= 5
Convergence Maximum Absolute= 0.001
Convergence RMSE= 0.0001
Grain Fractions Max Abs Error= 0.001
Max Subgrid Regions= 1
Max Subgrid Length Scale= 3.402823E+38
Initial Layer Thickness= 3.402823E+38
Min Layer Thickness= 3.402823E+38
Max Layer Thickness= 3.402823E+38
Number of Layers= 5

--- LIKANARV2A.f01 (steady flow) ---

Flow Title=Flows
Program Version=6.31
Number of Profiles= 1
Profile Names=01pct
River Rch & RM=LIKANARV2A,Main            ,3281
     609
River Rch & RM=LIKANARV2A,Main            ,0
    1140
Boundary for River Rch & Prof#=LIKANARV2A,Main            , 1
Up Type= 0
Dn Type= 1
Dn Known WS=1787
DSS Import GetInterval= 0
DSS Import GetPeak= 0
DSS Import FillOption= 0

--- LIKANARV2A.g01 (geometry) ---

Geom Title=Geometry
Program Version=6.31

River Reach=LIKANARV2A      ,Main
Reach XY= 30
     2175585.578      655204.073     2175488.741      655195.459
     2175428.932      655164.611     2175361.255      655219.898
     2175284.534      655191.711     2175184.377       655037.84
      2175070.77      654969.848     2174937.818      654999.952
      2174849.25      655105.833     2174783.862      655083.541
     2174694.121         655085.     2174621.092      655122.831
     2174512.006      655122.545     2174415.111      655162.808
     2174369.182      655159.603     2174331.751      655186.588
     2174141.767       655192.14     2173992.533      655149.616
     2173670.627      655286.145     2173624.526      655362.579
     2173418.288       655425.22      2173338.62      655425.535
     2173280.214      655403.615     2173238.348       655408.68
     2173188.212      655444.2792173090.07128702655447.928829981
     2172886.166      655394.028     2172839.893      655366.328
     2172797.026      655305.432 2172710.4180069655335.214725448

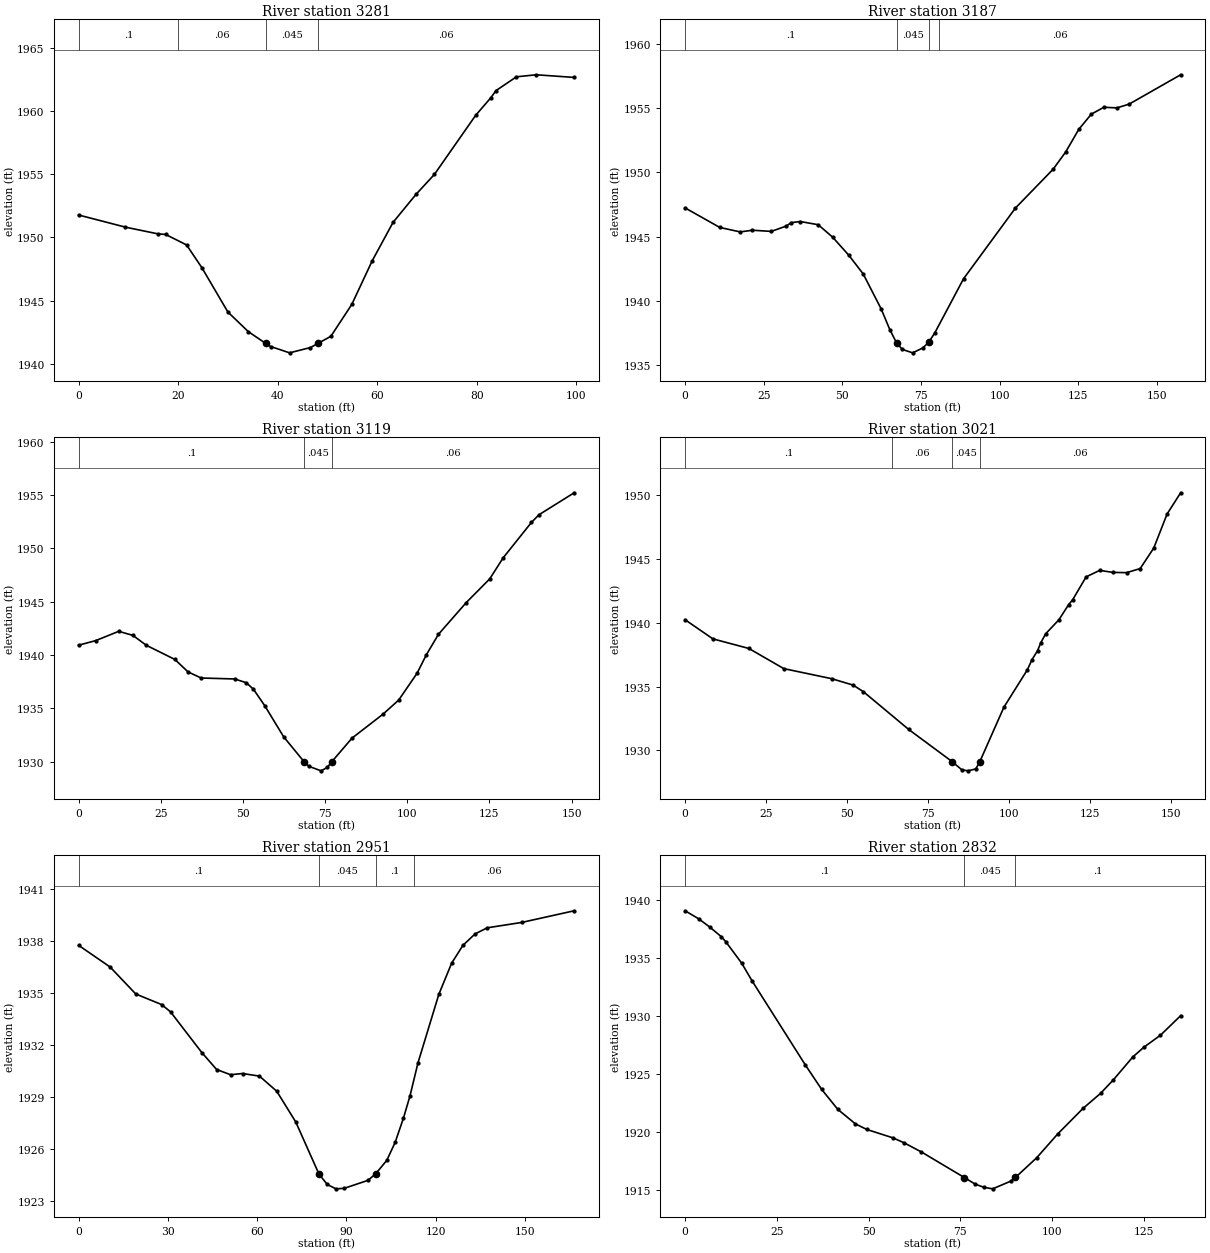
Type RM Length L Ch R = 1 ,3281    ,94.7,94.7,94.7
XS GIS Cut Line= 3
2175554.83432019655160.3025129022175532.62111404655240.042649586
2175535.31202424655256.679638154
#Sta/Elev= 25
       0 1951.77     9.4 1950.81    15.9 1950.28    17.5 1950.23    21.7  1949.4
    24.8 1947.58      30 1944.09    34.1 1942.54    37.61941.607    38.6 1941.36
    42.4 1940.86    46.6 1941.28    48.11941.606    50.7 1942.17    54.9 1944.69
      59 1948.14    63.2 1951.19    67.8  1953.4    71.5 1954.98    79.8 1959.66
    82.8 1961.03    83.9 1961.62      88 1962.71      92 1962.87    99.6 1962.66
#Mann= 4 ,-1,0
       0      .1       0      20     .06       0    37.6    .045       0
    48.1     .06       0
Bank Sta=37.6,48.1
XS Rating Curve= 0 ,0
Exp/Cntr(USF)=0,0
Exp/Cntr=0.3,0.1

Type RM Length L Ch R = 1 ,3187    ,82.5,67.8,54.7
XS GIS Cut Line= 6
2175505.56696318655124.1001305572175489.86915325655133.620365492
2175477.59862606655152.2377170942175444.59513912655194.549879826
2175449.05674914655246.9756302462175450.70301038655257.391757566
#Sta/Elev= 30
       0 1947.24      11 1945.72    17.5 1945.37    21.4  1945.5    27.4 1945.41
    32.2 1945.83    33.7 1946.09    36.6 1946.18    42.3 1945.93    46.9 1944.96
      52 1943.56    56.6  1942.1    62.3 1939.38    65.1 1937.74    67.2 1936.73
      69 1936.22    72.3 1935.95    75.5 1936.32    77.4 1936.76    79.4 1937.52
    88.5 1941.72     105 1947.23     117 1950.26     121 1951.61   125.1 1953.35
   129.1 1954.54   133.1 1955.08   137.2 1955.03   141.1 1955.32   157.5 1957.61
#Mann= 4 ,-1,0
       0      .1       0    67.2    .045       0    77.4      .1       0
   80.66     .06       0
Bank Sta=67.2,77.4
XS Rating Curve= 0 ,0
Exp/Cntr(USF)=0,0
Exp/Cntr=0.3,0.1

Type RM Length L Ch R = 1 ,3119    ,85.6,97.8,107.8
XS GIS Cut Line= 6
2175387.52846636655117.8186393282175377.31880038655143.775284547
2175378.58816526655161.1232712682175426.40090915655208.512893528
2175437.82519309655230.5152181492175440.90171041655243.611252486
#Sta/Elev= 30
       0 1940.92     5.2 1941.35    12.2 1942.22    16.5 1941.84    20.6 1940.91
    29.3 1939.58    33.3 1938.41    37.3 1937.84    47.5 1937.75      51  1937.4
    53.2 1936.79    56.7 1935.21    62.4 1932.32    68.61929.987      70 1929.56
    73.8 1929.13    75.7 1929.46      771929.969    83.2  1932.2    92.6 1934.44
    97.4 1935.77     103 1938.29   105.8 1940.01   109.5 1941.94   117.9  1944.9
   125.1 1947.14   129.2 1949.12   137.8 1952.44   140.1 1953.16   150.8 1955.22
#Mann= 3 ,-1,0
       0      .1       0    68.6    .045       0      77     .06       0
Bank Sta=68.6,77
XS Rating Curve= 0 ,0
Exp/Cntr(USF)=0,0
Exp/Cntr=0.3,0.1

Type RM Length L Ch R = 1 ,3021    ,63.6,69.8,76.5
XS GIS Cut Line= 5
2175370.54885434655131.9278789822175351.93150274655148.852744075
2175335.00663765655172.1244335782175314.69679954655219.937177466
2175301.15690746 655265.21119159
#Sta/Elev= 30
       0 1940.24     8.6 1938.74    19.7 1937.99    30.5 1936.41    45.3 1935.62
    51.9 1935.12    55.1  1934.6    69.1 1931.64    82.51929.123    85.5 1928.48
    87.4  1928.4    89.8 1928.55      911929.087    98.5 1933.39   105.7  1936.3
   107.2 1937.12   108.9 1937.82   109.9 1938.44   111.4 1939.14   115.5 1940.24
   118.5 1941.43   119.7 1941.79   123.9  1943.6   128.1 1944.11   132.2 1943.95
   136.4 1943.93   140.6 1944.25   144.8 1945.86   148.9 1948.52   153.1 1950.19
#Mann= 4 ,-1,0
       0      .1       0   63.94     .06       0    82.5    .045       0
      91     .06       0
Bank Sta=82.5,91
XS Rating Curve= 0 ,0
Exp/Cntr(USF)=0,0
Exp/Cntr=0.3,0.1

Type RM Length L Ch R = 1 ,2951    ,117.6,119.4,119.5
XS GIS Cut Line= 6
2175315.59203401655095.2908243972175302.47526356655128.294311329
2175287.24288498655150.7197575772175247.04633038655182.877001254
2175215.31220833655188.8007040362175197.11797836 655197.68625821
#Sta/Elev= 30
       0 1937.74    10.6 1936.49    19.2 1934.94    27.9 1934.33    30.9 1933.91
    41.4 1931.57    46.4 1930.59    51.1 1930.29    55.1 1930.36    60.8 1930.21
    66.6 1929.34      73 1927.57    80.8 1924.57    83.6 1923.97    86.5 1923.72
    89.3 1923.75    97.3 1924.21    99.91924.592   103.6 1925.36   106.4 1926.39
   109.2 1927.79   111.4 1929.07   114.1 1930.98   121.1 1934.92   125.4 1936.71
   129.2 1937.74   133.3  1938.4   137.4 1938.75     149 1939.06   166.6 1939.73
#Mann= 4 ,-1,0
       0      .1       0    80.8    .045       0    99.9      .1       0
  112.62     .06       0
Bank Sta=80.8,99.9
XS Rating Curve= 0 ,0
Exp/Cntr(USF)=0,0
Exp/Cntr=0.3,0.1

Type RM Length L Ch R = 1 ,2832    ,76,73.2,70.2
XS GIS Cut Line= 5
2175274.56193759655034.7860805752175255.75653193655041.838107697
2175223.78734231655056.4122970822175180.53490929655086.030810995
2175167.37112533 655110.00770321
#Sta/Elev= 30
       0 1939.04     3.7 1938.35     6.8 1937.62     9.9  1936.8    11.1 1936.37
    15.4 1934.54    18.2 1933.03    32.8 1925.75    37.2 1923.67    41.6 1921.95
    46.4  1920.7    49.5 1920.22    56.6  1919.5    59.6 1919.08    64.4 1918.28
    76.11916.078      79 1915.52    81.4 1915.24    83.8 1915.11    88.7 1915.77
      90 1916.09    95.8 1917.79   101.5 1919.83   108.4 1922.03   113.2 1923.33
   116.7  1924.5     122 1926.47     125  1927.3   129.5 1928.33     135 1930.01
#Mann= 3 ,-1,0
       0      .1       0    76.1    .045       0      90      .1       0
Bank Sta=76.1,90
XS Rating Curve= 0 ,0
Exp/Cntr(USF)=0,0
Exp/Cntr=0.3,0.1

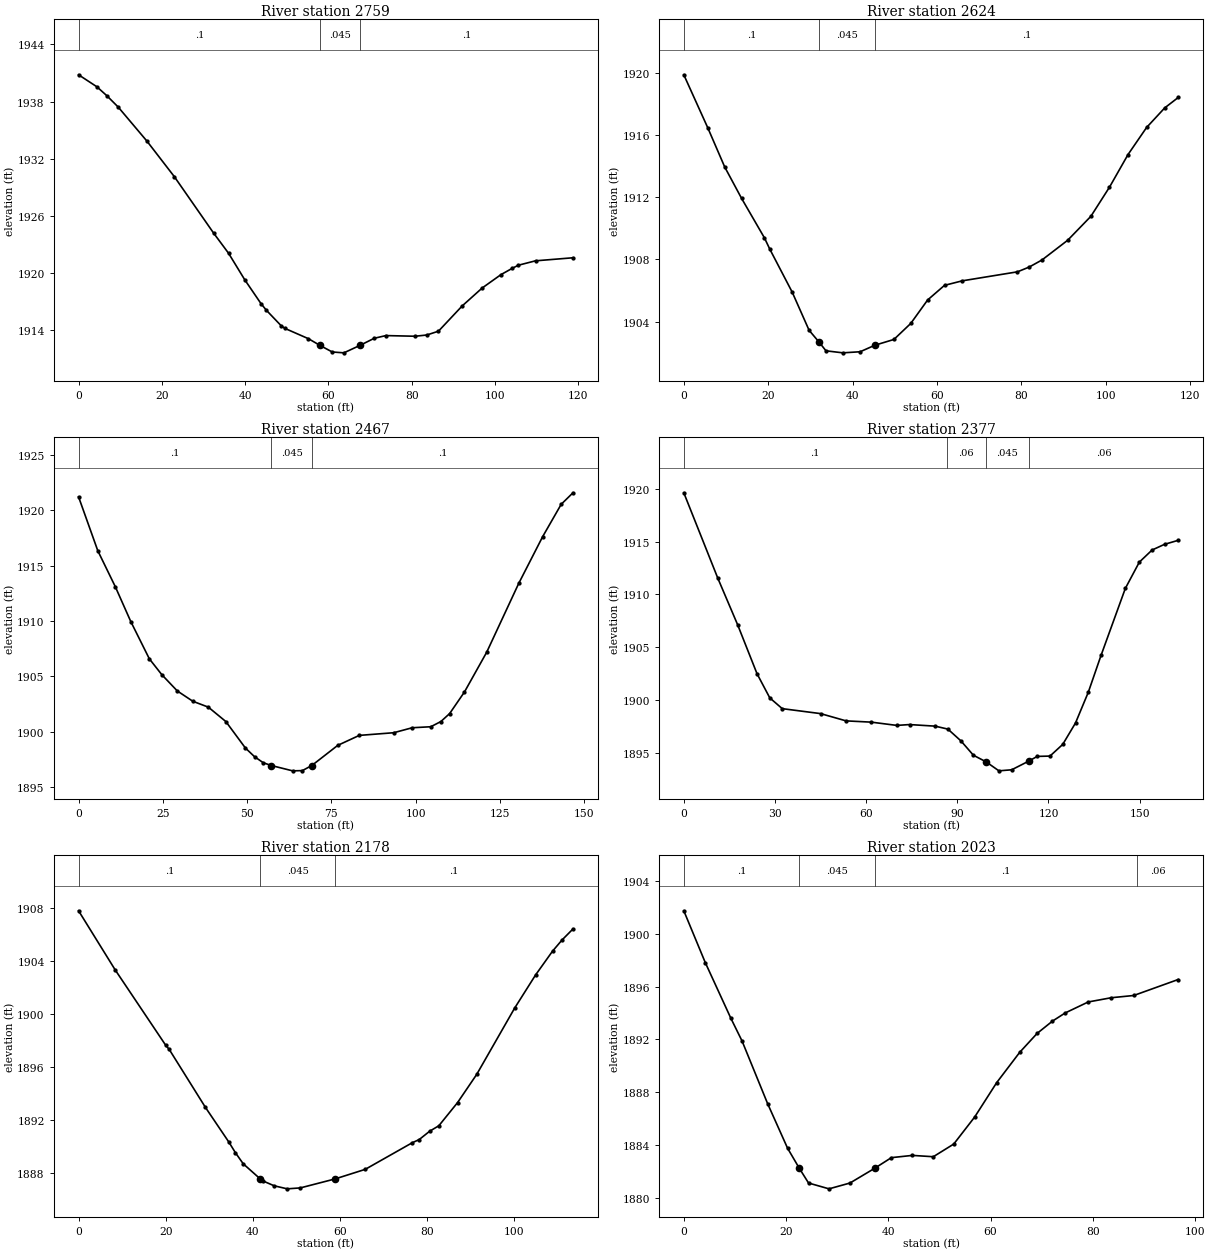
Type RM Length L Ch R = 1 ,2759    ,142.4,135.2,127.4
XS GIS Cut Line= 6
2175194.17439485654969.6712738792175178.40888302654990.234984967
2175170.25194538655000.5511121582175132.48991006655046.393178241
2175129.35099708655055.993757765 2175128.6730801655066.130090391
#Sta/Elev= 30
       0 1940.81     4.4 1939.55     6.8 1938.61     9.5 1937.43    16.4 1933.86
      23 1930.12    32.4 1924.22      36  1922.1    39.9 1919.31    43.8 1916.81
    45.1 1916.11    48.6 1914.51    49.5 1914.22    55.2 1913.13      58 1912.42
    60.9 1911.74    63.7 1911.65    67.5 1912.42      71 1913.18    73.8 1913.46
    80.8 1913.39    83.6 1913.52    86.4 1913.92    92.1 1916.57    96.9 1918.45
   101.4 1919.85   104.1 1920.51   105.6 1920.84   109.7  1921.3   118.7 1921.62
#Mann= 3 ,-1,0
       0      .1       0      58    .045       0    67.5      .1       0
Bank Sta=58,67.5
XS Rating Curve= 0 ,0
Exp/Cntr(USF)=0,0
Exp/Cntr=0.3,0.1

Type RM Length L Ch R = 1 ,2624    ,164.9,156.5,148.2
XS GIS Cut Line= 4
 2175036.7158762654939.4499109642175037.64124319654962.275630272
2175038.25815453655002.9917782262175059.85005117655052.036229171
#Sta/Elev= 28
       0 1919.87     5.7 1916.45     9.7 1913.94    13.7 1911.92    19.1 1909.39
    20.4 1908.65    25.7 1905.89    29.7 1903.44    32.1 1902.67    33.7 1902.12
    37.7 1901.99    41.8 1902.06    45.3 1902.48    49.8 1902.85    53.8 1903.88
    57.8 1905.39    61.8 1906.33      66 1906.62    79.1  1907.2    81.9 1907.51
    84.9 1907.96      91 1909.23    96.5 1910.77   100.9 1912.64   105.3 1914.74
   109.7 1916.48     114 1917.74   117.2 1918.41
#Mann= 3 ,-1,0
       0      .1       0    32.1    .045       0    45.3      .1       0
Bank Sta=32.1,45.3
XS Rating Curve= 0 ,0
Exp/Cntr(USF)=0,0
Exp/Cntr=0.3,0.1

Type RM Length L Ch R = 1 ,2467    ,83.1,90.1,94.2
XS GIS Cut Line= 3
2174869.78217916 654987.742545182174889.42593601655022.246762391
2174963.23826012655099.669335526
#Sta/Elev= 30
       0  1921.2     5.7 1916.34    10.9 1913.09    15.5 1909.94      21 1906.58
    24.7 1905.15    29.3 1903.68    33.9 1902.75    38.5 1902.22    43.7 1900.92
    49.5 1898.53    52.2 1897.75    54.8  1897.2    57.2 1896.95    63.5 1896.47
    66.4 1896.49    69.2 1896.95    76.9 1898.77    83.3 1899.67    93.5 1899.91
      99 1900.36   104.5 1900.45   107.5 1900.92   110.1 1901.64   114.5 1903.59
   121.1 1907.18   130.6 1913.39   137.7 1917.61   143.2 1920.53   146.7 1921.57
#Mann= 3 ,-1,0
       0      .1       0    57.2    .045       0    69.2      .1       0
Bank Sta=57.2,69.2
XS Rating Curve= 0 ,0
Exp/Cntr(USF)=0,0
Exp/Cntr=0.3,0.1

Type RM Length L Ch R = 1 ,2377    ,197.7,199.2,193.1
XS GIS Cut Line= 3
2174817.25226094655002.1099115572174830.62850874655046.592522365
2174865.70759667 655157.41992492
#Sta/Elev= 30
       0 1919.65    11.2 1911.54    17.7 1907.14    24.1 1902.48    28.3 1900.19
    32.4 1899.17      45  1898.7    53.4 1898.01    61.7 1897.89    70.1 1897.58
    74.3 1897.66    82.7 1897.51    86.9 1897.23    91.2 1896.11    95.3 1894.75
    99.5 1894.12   103.7 1893.27   107.9 1893.37   113.5 1894.19   116.3 1894.64
   120.5 1894.67   124.7 1895.78   128.9 1897.81   133.1 1900.72   137.3 1904.22
   145.3 1910.58   149.9 1913.07   154.1 1914.22   158.2 1914.76   162.7 1915.14
#Mann= 4 ,-1,0
       0      .1       0   86.45     .06       0    99.5    .045       0
   113.5     .06       0
Bank Sta=99.5,113.5
XS Rating Curve= 0 ,0
Exp/Cntr(USF)=0,0
Exp/Cntr=0.3,0.1

Type RM Length L Ch R = 1 ,2178    ,150.4,154.9,158
XS GIS Cut Line= 4
2174647.83180831655057.0468634912174655.85165564655087.583974457
2174679.54942838655134.4844687412174691.07272244655161.540980528
#Sta/Elev= 26
       0  1907.8     8.4 1903.34      20 1897.65    20.8 1897.34    29.1 1892.97
    34.5 1890.34      36 1889.54    37.8  1888.7    41.71887.561    42.3 1887.41
    44.9 1887.04    47.9 1886.81    50.9 1886.88    58.9 1887.56    65.8 1888.28
    76.6 1890.29    78.2 1890.53    80.6 1891.16    82.7 1891.57      87 1893.32
    91.4 1895.45   100.1 1900.45   104.9 1902.95   108.8 1904.75     111  1905.6
   113.5 1906.43
#Mann= 3 ,-1,0
       0      .1       0    41.7    .045       0    58.9      .1       0
Bank Sta=41.7,58.9
XS Rating Curve= 0 ,0
Exp/Cntr(USF)=0,0
Exp/Cntr=0.3,0.1

Type RM Length L Ch R = 1 ,2023    ,148.5,150.3,154.2
XS GIS Cut Line= 4
2174513.68702297655092.9666161182174512.76165597655109.314766433
2174520.47304763655150.9562813872174537.43810928655184.886404682
#Sta/Elev= 25
       0 1901.73     4.2 1897.81     9.2  1893.6    11.4 1891.87    16.4 1887.13
    20.3 1883.76    22.6 1882.24    24.4 1881.13    28.4 1880.69    32.5 1881.13
    37.31882.237    40.6 1883.05    44.7 1883.22    48.8 1883.12    52.8 1884.08
    56.9 1886.13    61.2 1888.73    65.7 1891.02    69.1 1892.45    72.1 1893.38
    74.6    1894    79.1 1894.83    83.6 1895.15      88 1895.32    96.7 1896.53
#Mann= 4 ,-1,0
       0      .1       0    22.6    .045       0    37.3      .1       0
   88.72     .06       0
Bank Sta=22.6,37.3
XS Rating Curve= 0 ,0
Exp/Cntr(USF)=0,0
Exp/Cntr=0.3,0.1

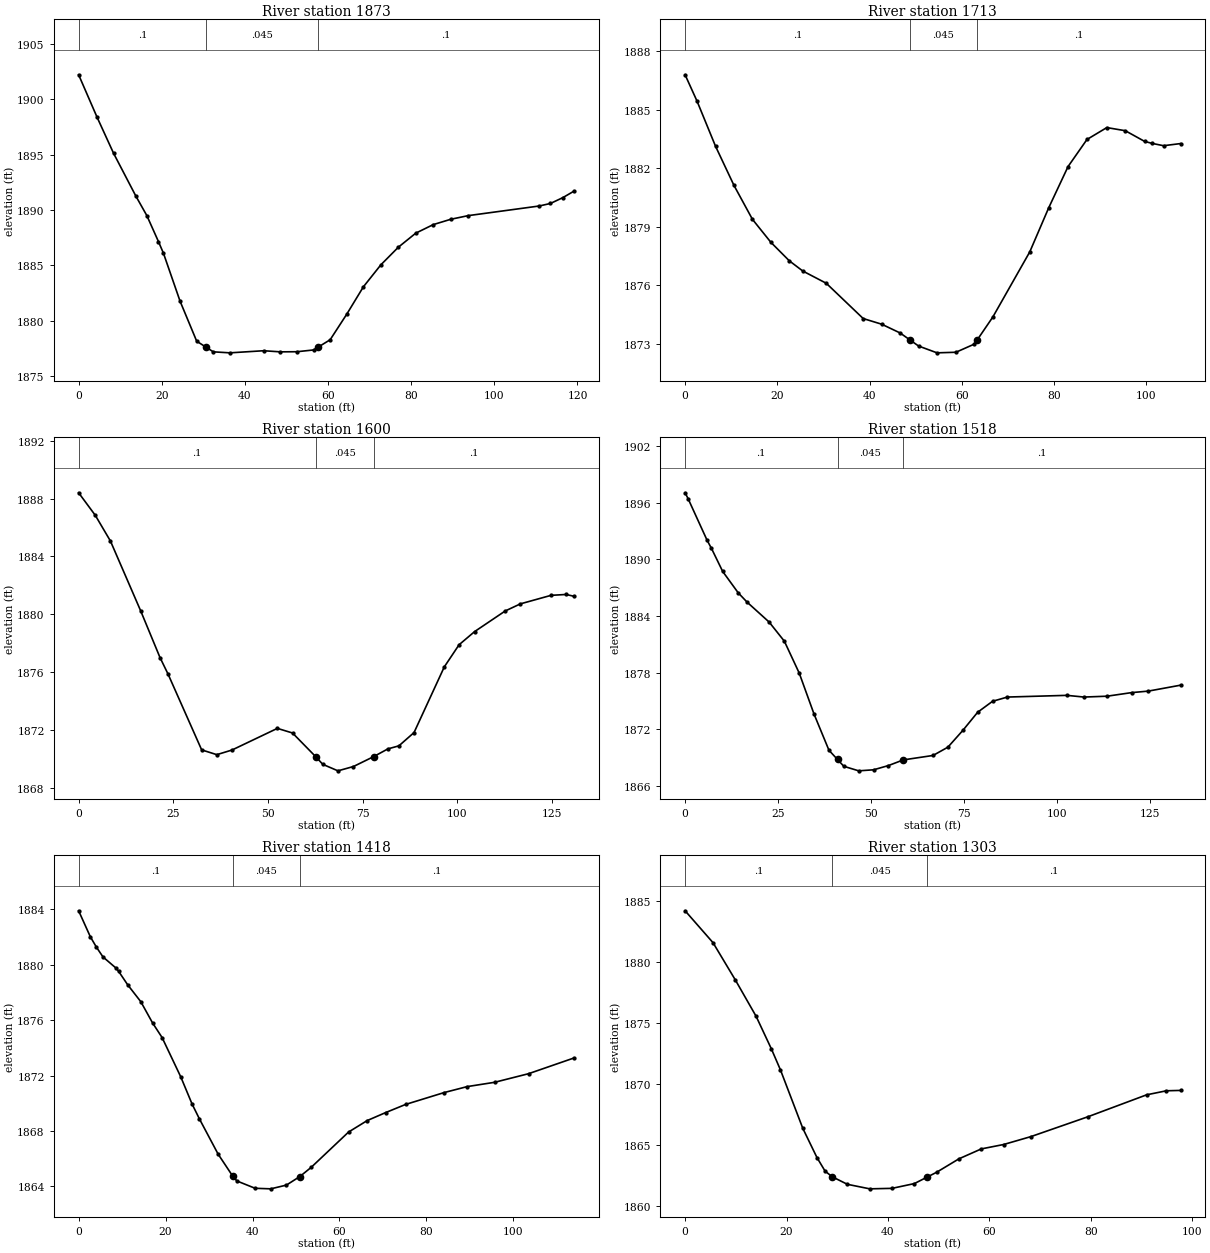
Type RM Length L Ch R = 1 ,1873    ,158,159.4,157
XS GIS Cut Line= 5
 2174374.1234725655120.797167671 2174373.2906422655142.173145347
2174377.17718359655190.7549127932174384.95026639655214.629381366
2174399.66360167655233.506868145
#Sta/Elev= 30
       0  1902.2     4.4  1898.4     8.4 1895.12    13.8 1891.23    16.4  1889.5
    19.2 1887.15    20.4  1886.1    24.4 1881.77    28.4 1878.16    30.71877.608
    32.4  1877.2    36.4 1877.11    44.5  1877.3    48.5  1877.2    52.5 1877.21
    56.5 1877.37    57.5  1877.6    60.5 1878.29    64.5  1880.6    68.5 1883.07
    72.7 1885.05    76.9 1886.64    81.1 1887.91    85.3 1888.68    89.5 1889.16
    93.7 1889.49   110.8 1890.36   113.5 1890.59   116.5 1891.12   119.2 1891.71
#Mann= 3 ,-1,0
       0      .1       0    30.7    .045       0    57.5      .1       0
Bank Sta=30.7,57.5
XS Rating Curve= 0 ,0
Exp/Cntr(USF)=0,0
Exp/Cntr=0.3,0.1

Type RM Length L Ch R = 1 ,1713    ,111.8,113.3,114.5
XS GIS Cut Line= 4
2174225.96821036655134.5727980422174225.21866309655162.056197912
 2174227.4673049 655208.278279512174236.21202304655240.758661174
#Sta/Elev= 29
       0  1886.8     2.6 1885.44     6.6 1883.13    10.6 1881.12    14.6 1879.38
    18.6  1878.2    22.6 1877.25    25.5 1876.73    30.6  1876.1    38.6 1874.29
    42.6    1874    46.6 1873.55    48.71873.198    50.6 1872.88    54.6 1872.53
    58.7 1872.56    62.7 1872.98    63.31873.189    66.7 1874.37    74.7 1877.71
    78.8 1879.97      83 1882.09    87.1 1883.48    91.4 1884.09    95.4 1883.93
    99.6 1883.38   101.2 1883.28   103.7 1883.16   107.4 1883.27
#Mann= 3 ,-1,0
       0      .1       0    48.7    .045       0    63.3      .1       0
Bank Sta=48.7,63.3
XS Rating Curve= 0 ,0
Exp/Cntr(USF)=0,0
Exp/Cntr=0.3,0.1

Type RM Length L Ch R = 1 ,1600    ,83.2,82.3,80.1
XS GIS Cut Line= 4
2174119.28264905655116.8335126722174116.78415815655143.067667093
2174112.03702545655218.0223940092174115.78476179655247.254737506
#Sta/Elev= 27
       0 1888.41     4.4 1886.85     8.4 1885.07    16.4 1880.23    21.5    1877
    23.6 1875.87    32.5 1870.61    36.5 1870.28    40.5  1870.6    52.5  1872.1
    56.5 1871.78    62.71870.119    64.5 1869.61    68.5 1869.16    72.6 1869.46
    77.9 1870.14    81.7 1870.68    84.6 1870.89    88.6 1871.81    96.6 1876.36
   100.5 1877.89   104.6  1878.8   112.7 1880.23   116.7 1880.72   124.8 1881.31
   128.8 1881.37   130.9 1881.24
#Mann= 3 ,-1,0
       0      .1       0    62.7    .045       0    77.9      .1       0
Bank Sta=62.7,77.9
XS Rating Curve= 0 ,0
Exp/Cntr(USF)=0,0
Exp/Cntr=0.3,0.1

Type RM Length L Ch R = 1 ,1518    ,103.4,99.4,94.1
XS GIS Cut Line= 6
2174047.47111075655103.5245517952174041.19740011655123.155194774
2174042.20928893655134.2859717212174042.61404445655181.439990424
2174043.22117774655209.7728771992174055.16146574655232.843942144
#Sta/Elev= 30
       0 1897.05      .8 1896.43     5.9 1892.03     7.1 1891.15    10.1 1888.72
    14.3 1886.44    16.7 1885.45    22.6 1883.35    26.7 1881.32    30.7 1877.94
    34.7 1873.58    38.7 1869.76      411868.783    42.7 1868.06    46.7 1867.58
    50.7 1867.69    54.7 1868.14    58.7 1868.74    66.7 1869.21    70.7 1870.09
    74.7 1871.86    78.7 1873.79    82.7 1874.95    86.7  1875.4   102.7 1875.58
   107.3  1875.4   113.5 1875.49   120.1 1875.87   124.6 1876.03   133.3 1876.66
#Mann= 3 ,-1,0
       0      .1       0      41    .045       0    58.7      .1       0
Bank Sta=41,58.7
XS Rating Curve= 0 ,0
Exp/Cntr(USF)=0,0
Exp/Cntr=0.3,0.1

Type RM Length L Ch R = 1 ,1418    ,116.1,115.4,114.6
XS GIS Cut Line= 6
2173927.58889777655129.9071364492173938.89979093655144.496549361
2173941.03082877655149.9061069572173958.24305748655194.657901617
2173974.96350823655221.0499856472173983.65158559655226.951321207
#Sta/Elev= 30
       0 1883.89     2.7 1882.01     4.1 1881.26     5.6 1880.56     8.5 1879.78
     9.2 1879.52    11.3 1878.54    14.3 1877.33      17  1875.8    19.2 1874.74
    23.5  1871.9    26.1 1869.94    27.8 1868.86    32.1 1866.32    35.4 1864.76
    36.4 1864.39    40.6 1863.86    44.2 1863.82    47.8 1864.09    50.9 1864.71
    53.5 1865.37    62.1 1867.92    66.4 1868.75    70.6 1869.32    75.2 1869.91
    84.1 1870.77    89.4  1871.2    95.7 1871.51   103.5 1872.13     114 1873.27
#Mann= 3 ,-1,0
       0      .1       0    35.4    .045       0    50.9      .1       0
Bank Sta=35.4,50.9
XS Rating Curve= 0 ,0
Exp/Cntr(USF)=0,0
Exp/Cntr=0.3,0.1

Type RM Length L Ch R = 1 ,1303    ,114.6,115.9,116.2
XS GIS Cut Line= 4
2173826.43986027655180.2380316712173833.86037823655195.528795962
2173854.54788286655240.9513604742173878.38348602655260.514544199
#Sta/Elev= 24
       0 1884.21     5.5  1881.6     9.9 1878.55      14 1875.57      17 1872.91
    18.8 1871.18    23.2  1866.4      26    1864    27.6 1862.89      29 1862.43
      32 1861.81    36.4 1861.44    40.8 1861.48    45.2 1861.87    47.71862.398
    49.6  1862.8      54  1863.9    58.4 1864.71    62.8 1865.07    68.2 1865.72
    79.4 1867.34      91 1869.14    94.9 1869.47    97.7  1869.5
#Mann= 3 ,-1,0
       0      .1       0      29    .045       0    47.7      .1       0
Bank Sta=29,47.7
XS Rating Curve= 0 ,0
Exp/Cntr(USF)=0,0
Exp/Cntr=0.3,0.1

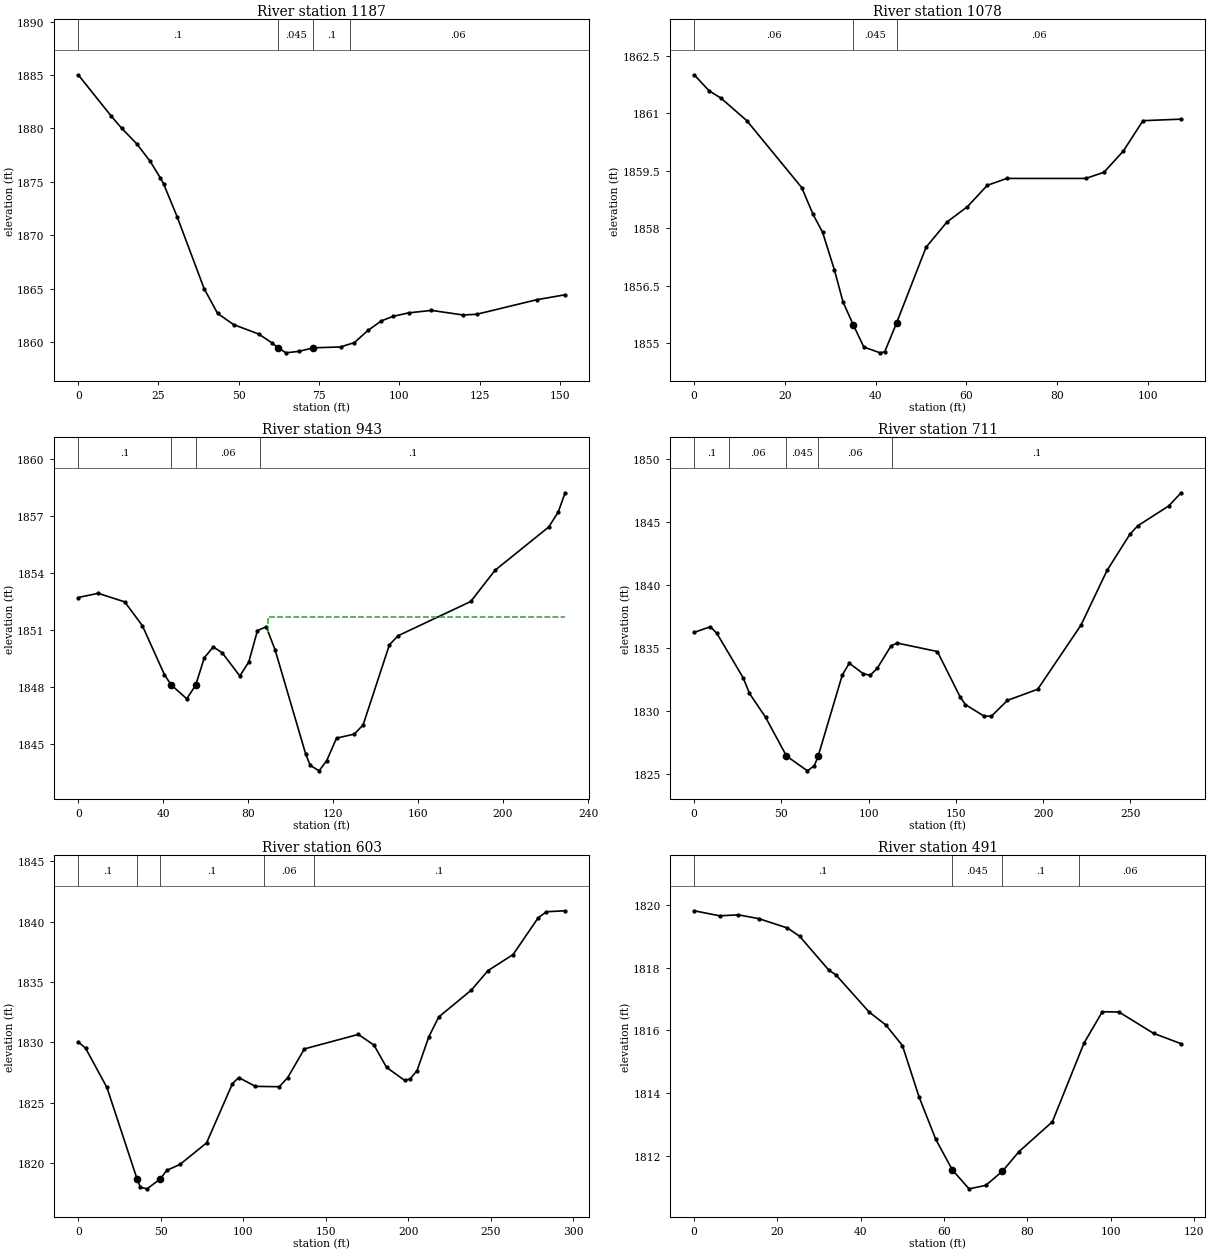
Type RM Length L Ch R = 1 ,1187    ,115.3,109.1,100.8
XS GIS Cut Line= 4
 2173716.7655373 655195.74346583 2173726.8489213655229.025651853
2173757.14603773655313.7523717052173782.86844498655321.397736306
#Sta/Elev= 28
       0 1885.02    10.3 1881.15    13.5 1880.03    18.2 1878.57    22.4 1876.93
    25.6 1875.36    26.6 1874.81    30.8 1871.75    39.2 1865.02    43.4  1862.7
    48.4 1861.65    56.2 1860.77    60.4 1859.93    62.21859.492    64.7 1859.01
    68.9 1859.16    73.2 1859.48    81.7 1859.56      86 1859.97    90.2  1861.1
    94.4    1862    98.1 1862.43   102.9 1862.75     110 1862.98   119.9 1862.55
   124.1 1862.62   142.8 1863.98   151.6 1864.44
#Mann= 4 ,-1,0
       0      .1       0    62.2    .045       0    73.2      .1       0
   84.78     .06       0
Bank Sta=62.2,73.2
XS Rating Curve= 0 ,0
Exp/Cntr(USF)=0,0
Exp/Cntr=0.3,0.1

Type RM Length L Ch R = 1 ,1078    ,125.1,134.6,141.2
XS GIS Cut Line= 4
2173620.43003776655288.2180128862173634.03293436655304.597010831
2173670.12225187655324.307330393 2173712.0413822655340.408718205
#Sta/Elev= 24
       0 1862.01     3.3 1861.59     5.9  1861.4    11.6 1860.81    23.7 1859.06
    26.2 1858.36    28.3 1857.89    30.9 1856.91    32.8 1856.07    35.1 1855.46
    37.4 1854.89      41 1854.74      42 1854.77    44.6 1855.52    51.1  1857.5
    55.7 1858.16    60.2 1858.56    64.6 1859.12    68.9  1859.3    86.3  1859.3
    90.3 1859.46    94.6 1860.02    98.9 1860.81   107.3 1860.85
#Mann= 3 ,-1,0
       0     .06       0    35.1    .045       0    44.6     .06       0
Bank Sta=35.1,44.6
XS Rating Curve= 0 ,0
Exp/Cntr(USF)=0,0
Exp/Cntr=0.3,0.1

Type RM Length L Ch R = 1 ,943     ,219,232.2,230.3
XS GIS Cut Line= 4
2173536.69363679655332.1702558782173558.11090705655404.780025793
2173583.40486292655499.8921851952173610.34815159655547.910075845
#Sta/Elev= 30
       0 1852.72     9.4 1852.94    21.9 1852.49    30.2 1851.24    40.6 1848.66
    43.7 1848.13    51.1 1847.39    55.3 1848.11    59.4 1849.56    63.6 1850.12
    67.8 1849.81    76.1 1848.59    80.3 1849.33    84.4 1850.98    88.5 1851.18
    92.7 1849.96   107.1 1844.48   109.2 1843.89   113.4  1843.6     117 1844.14
   121.6 1845.32   129.9 1845.53   134.1 1846.01   146.5 1850.23   150.6 1850.71
   184.8 1852.51   196.2 1854.15   221.5 1856.43     226 1857.22   229.2 1858.23
#Mann= 4 ,-1,0
       0      .1       0    43.7    .045       0    55.3     .06       0
    85.7      .1       0
#XS Ineff= 2 , 0
                           89.37         1851.68
Permanent Ineff=
       F       F
Bank Sta=43.7,55.3
XS Rating Curve= 0 ,0
Exp/Cntr(USF)=0,0
Exp/Cntr=0.3,0.1

Type RM Length L Ch R = 1 ,711     ,106.6,108,106.2
XS GIS Cut Line= 4
2173359.24094109655365.348814185 2173342.0026504655391.989808894
2173343.63587477655473.4927430292173414.08769941655623.663483992
#Sta/Elev= 30
       0 1836.24     9.3 1836.69      13 1836.16    28.1 1832.63    31.7 1831.39
    40.9  1829.5    52.9 1826.42    64.9 1825.24    68.9 1825.65    71.11826.428
    84.9 1832.85    88.9 1833.79    96.9 1832.96   100.9 1832.83   104.9 1833.38
   112.9 1835.18   116.4 1835.39   139.4 1834.72   152.5  1831.1   155.5  1830.5
   165.9 1829.61   170.3 1829.57   179.6 1830.84   196.9 1831.72   221.7 1836.81
   236.7 1841.17   249.9 1844.06   254.3 1844.71     272 1846.28   279.1 1847.33
#Mann= 5 ,-1,0
       0      .1       0      20     .06       0    52.9    .045       0
    71.1     .06       0  113.25      .1       0
Bank Sta=52.9,71.1
XS Rating Curve= 0 ,0
Exp/Cntr(USF)=0,0
Exp/Cntr=0.3,0.1

Type RM Length L Ch R = 1 ,603     ,110.1,112.2,111.2
XS GIS Cut Line= 4
2173246.03750015655368.9656782742173238.54202652655388.398387701
2173245.22377862655469.9228724582173363.10084031655622.098267223
#Sta/Elev= 30
       0 1830.05     4.5 1829.51    17.4 1826.27    35.71818.688    37.7 1818.01
    41.7 1817.88    49.7 1818.69    53.7 1819.41    61.7  1819.9    77.8 1821.68
    93.5 1826.59    97.3 1827.09   107.4 1826.36   121.9 1826.33     127 1827.09
   137.1 1829.46   169.8 1830.66   179.3 1829.77   186.9 1827.93   197.8 1826.86
   201.1 1826.97   205.4 1827.67   212.5 1830.46   218.5  1832.1   238.3 1834.33
   248.4 1835.94   263.6 1837.27   278.8 1840.31   283.8 1840.81   295.1 1840.89
#Mann= 5 ,-1,0
       0      .1       0    35.7    .045       0    49.7      .1       0
  112.63     .06       0  142.63      .1       0
Bank Sta=35.7,49.7
XS Rating Curve= 0 ,0
Exp/Cntr(USF)=0,0
Exp/Cntr=0.3,0.1

Type RM Length L Ch R = 1 ,491     ,142,145.4,147.8
XS GIS Cut Line= 3
2173157.69434638655387.9610072582173140.83762404655415.566133825
2173140.45442394655500.146027068
#Sta/Elev= 24
       0 1819.81     6.1 1819.65    10.6 1819.68    15.5 1819.56    22.4 1819.26
    25.3    1819    32.3 1817.92      34 1817.77      42 1816.58      46 1816.17
      50 1815.51      54 1813.87      58 1812.52      62 1811.54      66 1810.94
      70 1811.05      74  1811.5      78 1812.13      86 1813.08    93.6 1815.59
      98 1816.59     102 1816.58   110.3  1815.9   116.9 1815.57
#Mann= 4 ,-1,0
       0      .1       0      62    .045       0      74      .1       0
   92.34     .06       0
Bank Sta=62,74
XS Rating Curve= 0 ,0
Exp/Cntr(USF)=0,0
Exp/Cntr=0.3,0.1

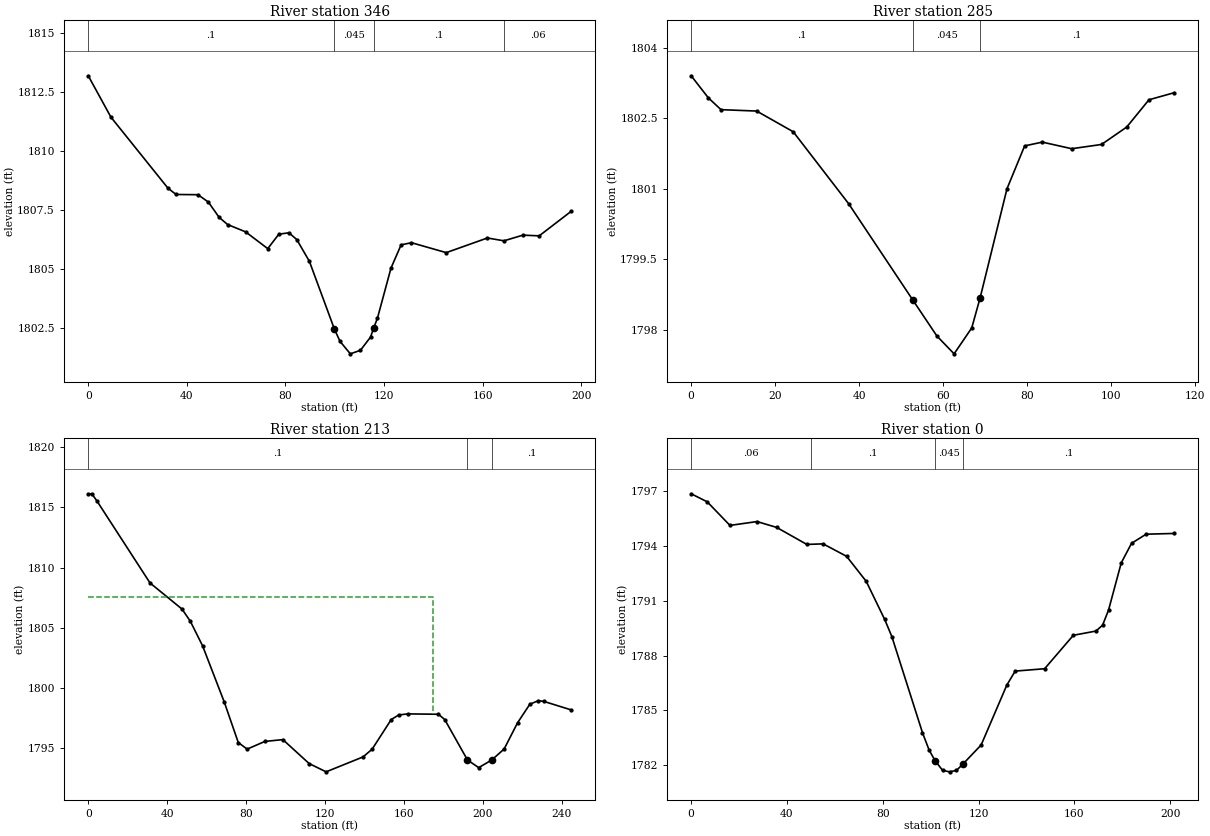
Type RM Length L Ch R = 1 ,346     ,60,60.8,61.2
XS GIS Cut Line= 5
2173076.56333832655354.8163797962173010.21516409655384.894218784
2172994.85413163655442.6954261262173010.02498377655475.239310238
2173031.66920961655491.980836104
#Sta/Elev= 30
       0 1813.18     9.2 1811.43    32.3 1808.43    35.6 1808.16    44.5 1808.15
    48.7 1807.84    53.1 1807.19    56.5 1806.89    63.8 1806.58    72.8 1805.87
    77.3 1806.48    81.4 1806.54    84.6 1806.25    89.7 1805.33    99.81802.477
   102.1 1801.95   106.3 1801.42   110.4 1801.57   114.5 1802.13   115.71802.494
   117.3 1802.93   122.8 1805.05   126.9 1806.03   131.1 1806.12   145.2  1805.7
   161.9 1806.32   168.6  1806.2   176.3 1806.44   182.9 1806.41   195.9 1807.45
#Mann= 4 ,-1,0
       0      .1       0    99.8    .045       0   115.7      .1       0
  168.56     .06       0
Bank Sta=99.8,115.7
XS Rating Curve= 0 ,0
Exp/Cntr(USF)=0,0
Exp/Cntr=0.3,0.1

Type RM Length L Ch R = 1 ,285     ,72.1,72.1,73.2
XS GIS Cut Line= 5
2172982.83947709655359.6829594182172958.97038531655368.945630595
2172952.65085607655372.9671491982172935.53395044655427.904599211
2172951.67789376655446.169171657
#Sta/Elev= 19
       0  1803.4     4.1 1802.93     7.1 1802.68    15.6 1802.65    24.3 1802.21
    37.5 1800.68    52.8 1798.63    58.5 1797.87    62.6 1797.49    66.8 1798.04
    68.8 1798.68    75.2    1801    79.4 1801.91    83.6 1801.99    90.6 1801.85
    97.7 1801.94   103.7 1802.31     109 1802.89     115 1803.04
#Mann= 3 ,-1,0
       0      .1       0    52.8    .045       0    68.8      .1       0
Bank Sta=52.8,68.8
XS Rating Curve= 0 ,0
Exp/Cntr(USF)=0,0
Exp/Cntr=0.3,0.1

Type RM Length L Ch R = 1 ,213     ,140.3,212.7,127.1
XS GIS Cut Line= 4
2173025.07384449655271.8345616362172993.42083466655307.208813827
2172883.27118815655365.0631744182172856.42895195655432.701127892
#Sta/Elev= 30
       0 1816.09     1.8 1816.14     4.4 1815.54    31.3 1808.72    47.5 1806.55
    51.7 1805.54    57.9  1803.5    68.9 1798.82      76 1795.45    80.5  1794.9
    89.5 1795.54    98.6 1795.69   111.9  1793.7   120.5 1793.01   139.2 1794.25
   143.8 1794.89   153.5 1797.36   157.3 1797.74   161.8 1797.83   177.4  1797.8
   180.6 1797.36   192.11794.002   197.8 1793.36   204.41793.993   210.7 1794.91
   217.5 1797.09   223.7 1798.63     228 1798.93   230.8 1798.87   244.7 1798.16
#Mann= 3 ,-1,0
       0      .1       0   192.1    .045       0   204.4      .1       0
#XS Ineff= 2 , 0
          174.72 1807.55
Permanent Ineff=
       F       F
Bank Sta=192.1,204.4
XS Rating Curve= 0 ,0
Exp/Cntr(USF)=0,0
Exp/Cntr=0.3,0.1

Type RM Length L Ch R = 1 ,0       ,187.2,186.1,188.4
XS GIS Cut Line= 4
2172662.55044757 655242.757111962172681.63425048655309.847080259
2172729.90710475 655352.39081992 2172780.8461831655396.887590316
#Sta/Elev= 30
       0 1796.85     6.7 1796.41    16.2 1795.12    27.5 1795.33    35.7 1795.01
    48.3 1794.08    55.1 1794.11    64.9 1793.43    73.1 1792.06    80.8 1789.98
    83.8 1789.04    96.6 1783.78    99.4 1782.82   101.91782.242     105 1781.72
   107.9 1781.64   110.8 1781.72   113.51782.067   121.1 1783.11   131.8 1786.38
   135.3 1787.15   147.6 1787.28   159.6 1789.11     169 1789.34   171.8 1789.66
   174.3 1790.49   179.6 1793.07   183.9 1794.14     190 1794.64   201.7 1794.68
#Mann= 4 ,-1,0
       0     .06       0      50      .1       0   101.9    .045       0
   113.5      .1       0
Bank Sta=101.9,113.5
XS Rating Curve= 0 ,0
Exp/Cntr=0.3,0.1
LCMann Table=0

Chan Stop Cuts=-1
Use User Specified Reach Order=0
Composite Channel Slope=5